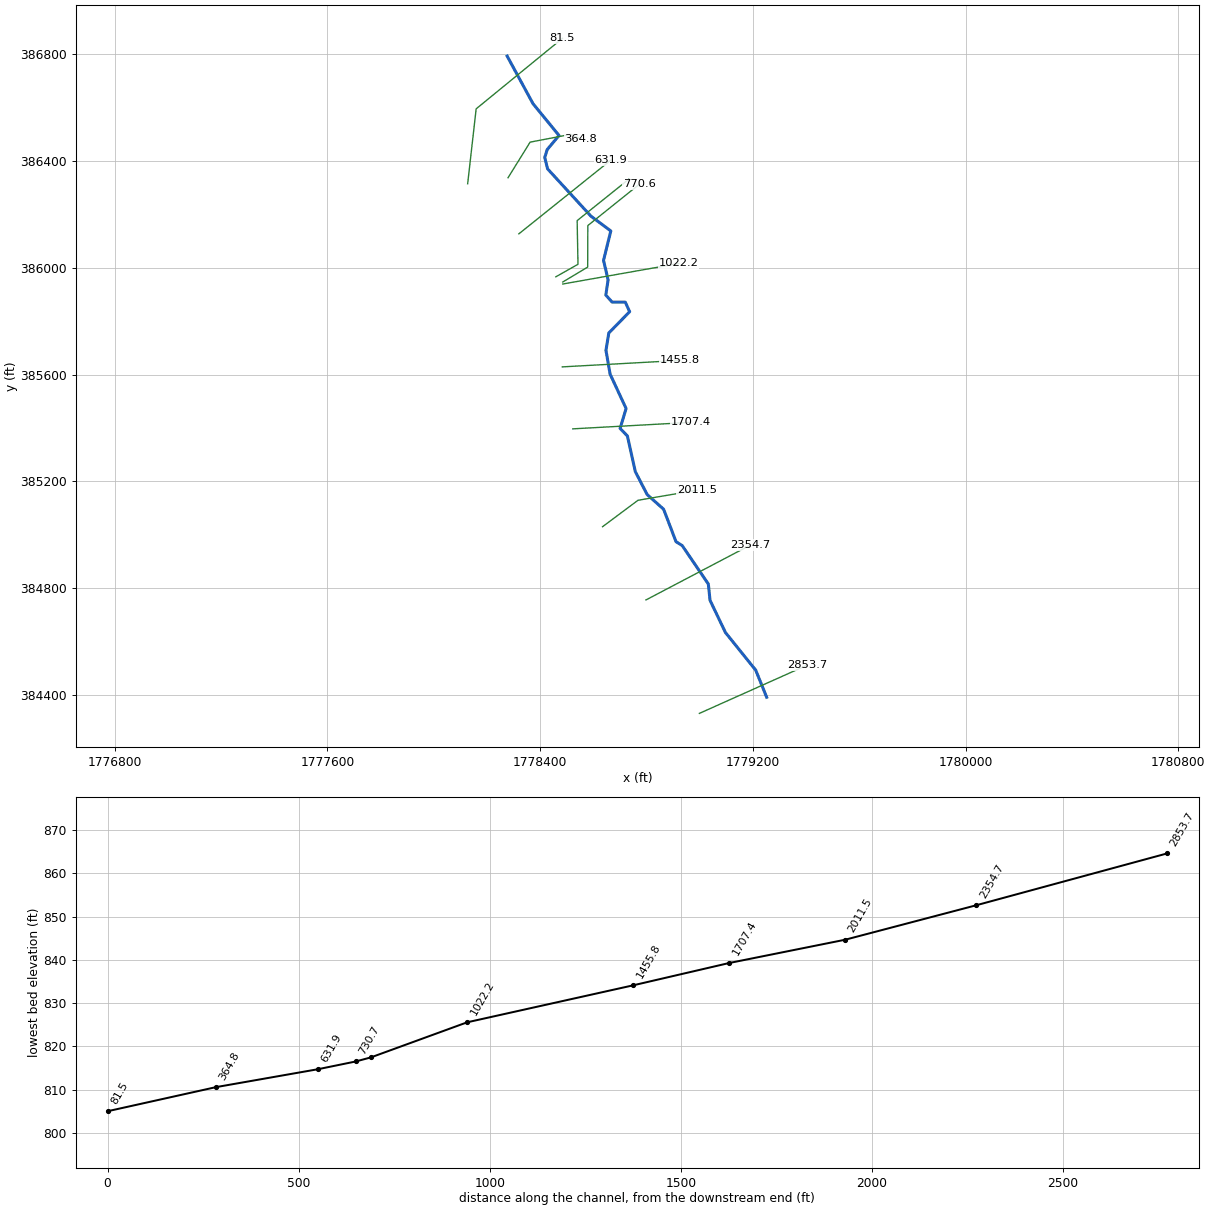
--- COLDFORK.prj (project) ---

Proj Title=COLDFORK
Current Plan=p01
Default Exp/Contr=0,0
English Units
Geom File=g01
Flow File=f01
Plan File=p01
BEGIN DESCRIPTION:
END DESCRIPTION:
DSS Export Rating Curves= 0
DSS Export Rating Curve Sorted= 0
DSS Export Volume Flow Curves= 0
DXF OffsetX= 0
DXF OffsetY= 0
DXF ScaleX= 0
DXF ScaleY= 0

--- COLDFORK.p01 (plan) ---

Plan Title=Floodplain
Program Version=4.00
Geom File=g01
Flow File=f01
K Sum by GR=0
Std Step Tol=0.01
Critical Tol=0.01
Num of Std Step Trials=20
Max Error Tol=0.3
Flow Tol Ratio=0.001
Split Flow NTrial=30
Split Flow Tol=0.02
Split Flow Ratio=0.02
Log Output Level=0
Friction Slope Method=1
Unsteady Friction Slope Method=2
Unsteady Bridges Friction Slope Method=1
Global Log Level=0
CheckData=False
Run HTab=0
Run UNet=0
Run PostProcess=0
UNET Theta=0
UNET Theta Warmup=0
UNET ZTol=0
UNET ZSATol=0
UNET MxIter=0
UNET MaxInSteps=0
UNET DtIC=0
UNET DtMin=0
UNET MaxCRTS=0
UNET WFStab=0
UNET SFStab=0
UNET WFX=0
UNET SFX=0
UNET DSS MLevel=0
UNET DZMax Abort=0
UNET Convert EG Bridges=0
UNET Use Existing IB Tables=0
UNET Froude Limit=0
UNET Froude Power=0
Write IC File=0
Echo Input=False
Echo Output=False
Write Detailed=0

--- COLDFORK.f01 (steady flow) ---

Flow Title=NFF Regression Equation
Program Version=4.00
Number of Profiles=1
Profile Names=P100yr
River Rch & RM=COLDFORK,Main      ,2853.7
884.7436
River Rch & RM=COLDFORK,Main      ,364.8
943.0368
River Rch & RM=COLDFORK,Main      ,81.5
944.7063
Boundary for River Rch & Prof#=COLDFORK,Main      ,1
Up Type=0
Dn Type=3
Dn Slope=0.017768

--- COLDFORK.g01 (geometry) ---

Geom Title=USGS 10m DEM
Program Version=4.10

River Reach=COLDFORK        ,Main
Reach XY= 30
     1779251.817      384390.449     1779210.888      384491.817
     1779097.018      384632.761     1779038.889      384753.797
     1779032.519      384814.872     1778934.098      384959.001
     1778911.005      384973.334     1778864.309      385095.079
      1778802.51      385149.892     1778757.907      385235.873
     1778728.029      385369.788     1778700.665      385397.796
     1778723.192      385472.536     1778663.006      385601.507
     1778647.422      385690.712     1778658.169      385755.735
     1778736.627      385835.375     1778719.968       385871.38
     1778670.529       385871.38     1778646.884      385897.711
     1778655.482      385954.673     1778638.286      386027.757
     1778665.692      386138.028     1778590.997      386193.378
     1778427.848      386370.712     1778417.208      386413.274
     1778426.343      386442.831     1778470.869      386495.836
     1778373.142      386614.792     1778275.876      386793.203

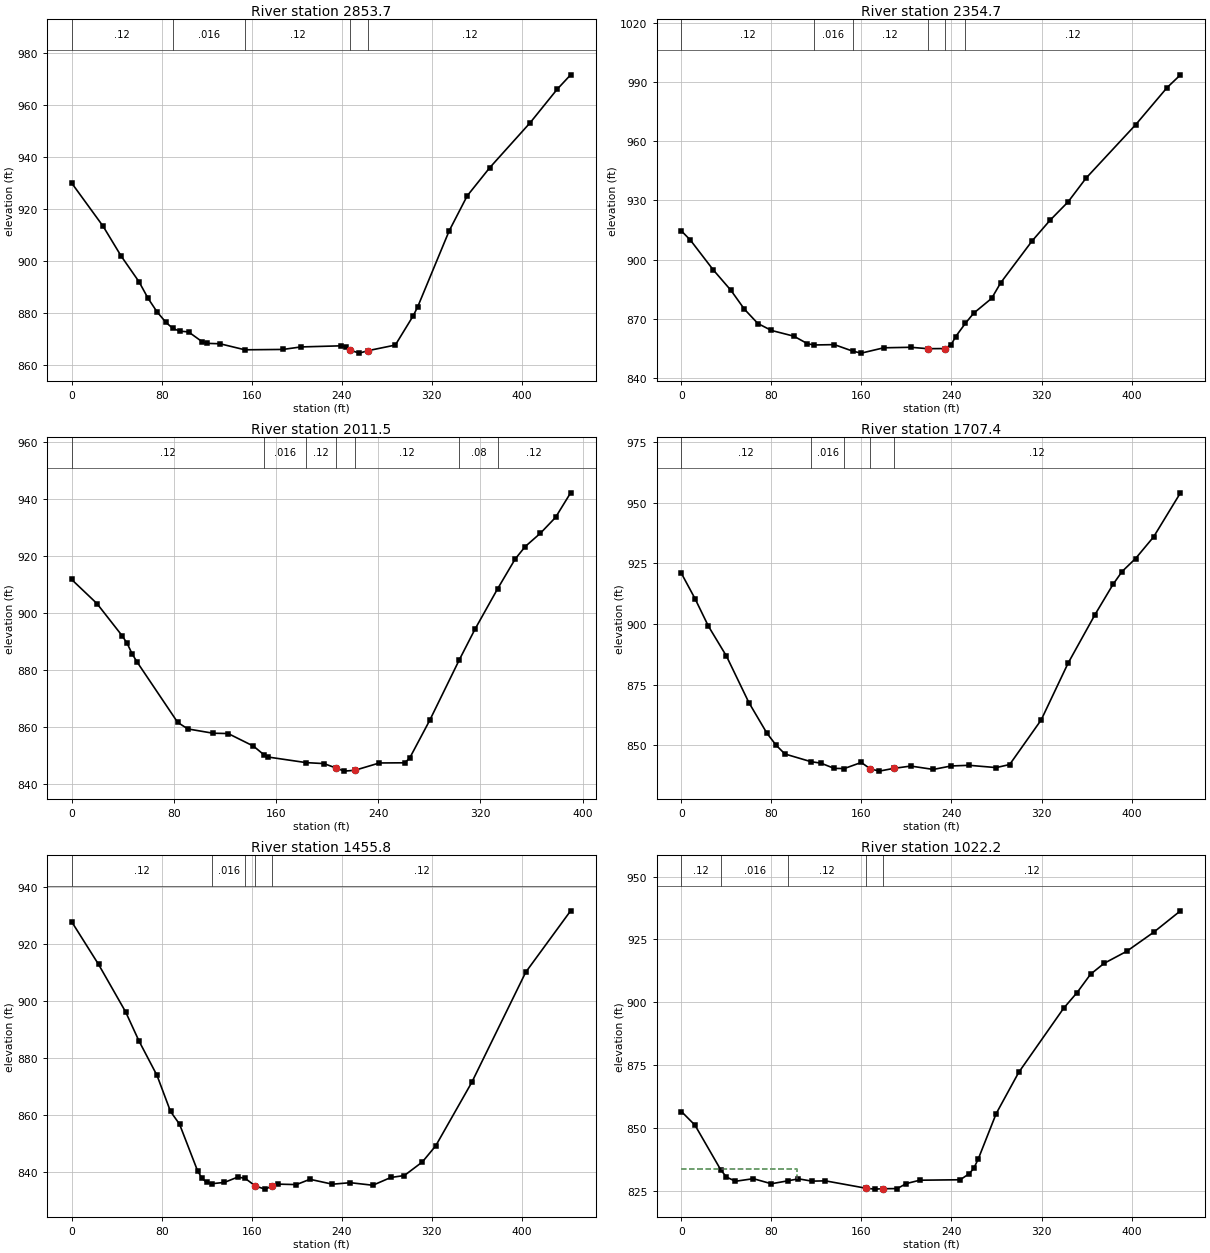
Type RM Length L Ch R = 1 ,2853.7  ,497.1,498.9,500.7
XS GIS Cut Line= 2
     1778998.943         384330.     1779404.021      384510.632
#Sta/Elev= 30
       0  930.05      28   913.4      44  901.97    59.9  892.08    67.9  885.74
    75.9  880.51    83.9  876.44   89.78874.1989    95.9   873.1   103.9   872.8
   115.9  869.06   119.9   868.4   131.9  868.24  154.01865.9158   187.8  866.06
   203.8  867.02   239.7  867.45   243.7  867.06   247.7  865.74   255.7  864.64
   263.7  865.61   287.7  867.74   303.7  879.06   307.7  882.56   335.6  911.68
   351.6  925.11   371.6  935.92   407.6  953.24   431.5  966.05   443.5  971.62
#Mann= 5 ,-1 , 0
       0     .12       0   89.78    .016       0  154.01     .12       0
   247.7    .045       0   263.7     .12       0
Bank Sta=247.7,263.7
XS Rating Curve= 0 ,0
Exp/Cntr=0.3,0.1

Type RM Length L Ch R = 1 ,2354.7  ,352.6,343.3,333.5
XS GIS Cut Line= 2
     1778797.925      384755.104     1779190.875      384960.788
#Sta/Elev= 30
       0  914.52       8  909.85      28     895      44  884.44    55.9  874.94
    67.9  867.66    79.9  864.16    99.9  861.24   111.9  857.46  117.52856.7836
   135.9  856.97   152.3853.6487   159.8  852.66   179.8  855.36   203.8  855.62
   218.9  854.91   233.9  854.97   239.7   856.9   243.7  861.03  252.32 867.728
   259.7  872.88   275.7  880.41   283.7  888.26   311.7  909.52   327.6  919.96
   343.6  929.24   359.6   941.3   403.6  968.28   431.5  987.07   443.5   993.6
#Mann= 6 ,-1 , 0
       0     .12       0  117.52    .016       0   152.3     .12       0
   218.9    .045       0   233.9     .08       0  252.32     .12       0
Bank Sta=218.9,233.9
XS Rating Curve= 0 ,0
Exp/Cntr=0.3,0.1

Type RM Length L Ch R = 1 ,2011.5  ,304.7,304.1,302.4
XS GIS Cut Line= 3
     1778634.654      385029.588     1778767.869      385128.604
     1778989.287      385166.371
#Sta/Elev= 30
       0  911.87    19.8  903.44    39.5  892.17    43.5  889.44    47.4  885.76
    51.4  882.83      83  861.78    90.9  859.48   110.7  857.97   122.5  857.86
   142.3  853.46  150.76850.3365   154.1   849.6  183.55847.6653   197.5  847.32
   206.7  845.82   213.3  844.68   221.7  844.97   240.9  847.54   260.6   847.6
   264.5  849.16   280.3  862.49   303.4883.6469   315.7   894.4  333.37908.5455
   347.2  919.05   355.1  923.43     367  928.11   378.8  933.64   390.6  942.25
#Mann= 7 ,-1 , 0
       0     .12       0  150.76    .016       0  183.55     .12       0
   206.7    .045       0   221.7     .12       0   303.4     .08       0
  333.37     .12       0
Bank Sta=206.7,221.7
XS Rating Curve= 0 ,0
Exp/Cntr=0.3,0.1

Type RM Length L Ch R = 1 ,1707.4  ,251.7,251.6,251.5
XS GIS Cut Line= 2
     1778522.474      385396.324     1778965.337      385420.588
#Sta/Elev= 30
       0  920.83      12  910.49      24  899.04      40  886.73    59.9  867.58
    75.9  854.97    83.9   850.1    91.9  846.36  115.21843.1621   123.9  842.58
   135.8   840.4  144.79840.3568   159.8  842.86   167.8  840.23   175.8  839.28
   188.5   840.4   203.8  841.37   223.8  839.98   239.7  841.41   255.7  841.68
   279.7  840.74   291.7     842   319.7  860.39   343.6   883.8   367.6   903.9
   383.6  916.35   391.6  921.63   403.6     927   419.6   935.9   443.5   954.1
#Mann= 5 ,-1 , 0
       0     .12       0  115.21    .016       0  144.79     .12       0
   167.8    .045       0   188.5     .12       0
Bank Sta=167.8,188.5
XS Rating Curve= 0 ,0
Exp/Cntr=0.3,0.1

Type RM Length L Ch R = 1 ,1455.8  ,428.1,433.6,436.9
XS GIS Cut Line= 2
     1778483.405      385628.596     1778926.267      385652.861
#Sta/Elev= 30
       0     928      24  912.96      48  896.33    59.9  886.09    75.9  874.02
    87.9  861.37    95.9  856.93   111.9  840.58   115.9  837.92   119.9   836.5
  124.76836.0193   135.8  836.47   147.8  838.36  154.34  837.86   163.3  835.21
   171.8  834.11   178.3  835.14   183.8  835.86   199.8   835.7   211.8  837.56
   231.8  835.84   247.7  836.37   267.7  835.47   283.7   838.2   295.7  838.88
   311.7  843.64   323.6  849.31   355.6  871.56   403.6  910.25   443.5   931.8
#Mann= 5 ,-1 , 0
       0     .12       0  124.76    .016       0  154.34     .12       0
   163.3    .045       0   178.3     .12       0
Bank Sta=163.3,178.3
XS Rating Curve= 0 ,0
Exp/Cntr=0.3,0.1

Type RM Length L Ch R = 1 ,1022.2  ,239.3,251.6,263.1
XS GIS Cut Line= 2
     1778484.929      385939.123     1778921.718      386016.138
#Sta/Elev= 30
       0  856.46      12  851.05   34.98 833.206      40  830.37      48   828.7
    63.9  829.73    79.9  827.71   94.97828.9112   103.9  829.67   115.9  828.75
   127.9  828.87     164  825.93   171.8  825.57     179  825.73   191.8  825.79
   199.8  827.78   211.8  829.12   247.7   829.3   255.7  831.69   259.7   833.8
   263.7  837.47   279.7  855.63   299.7  872.03   339.6  897.56   351.6  903.83
   363.6  911.15   375.6  915.47   395.6  920.24   419.6  927.83   443.5  936.39
#Mann= 5 ,-1 , 0
       0     .12       0   34.98    .016       0   94.97     .12       0
     164    .045       0     179     .12       0
#XS Ineff= 2 , 0
          102.88  833.43
Permanent Ineff=
       F       F
Bank Sta=164,179
XS Rating Curve= 0 ,0
Exp/Cntr=0.3,0.1

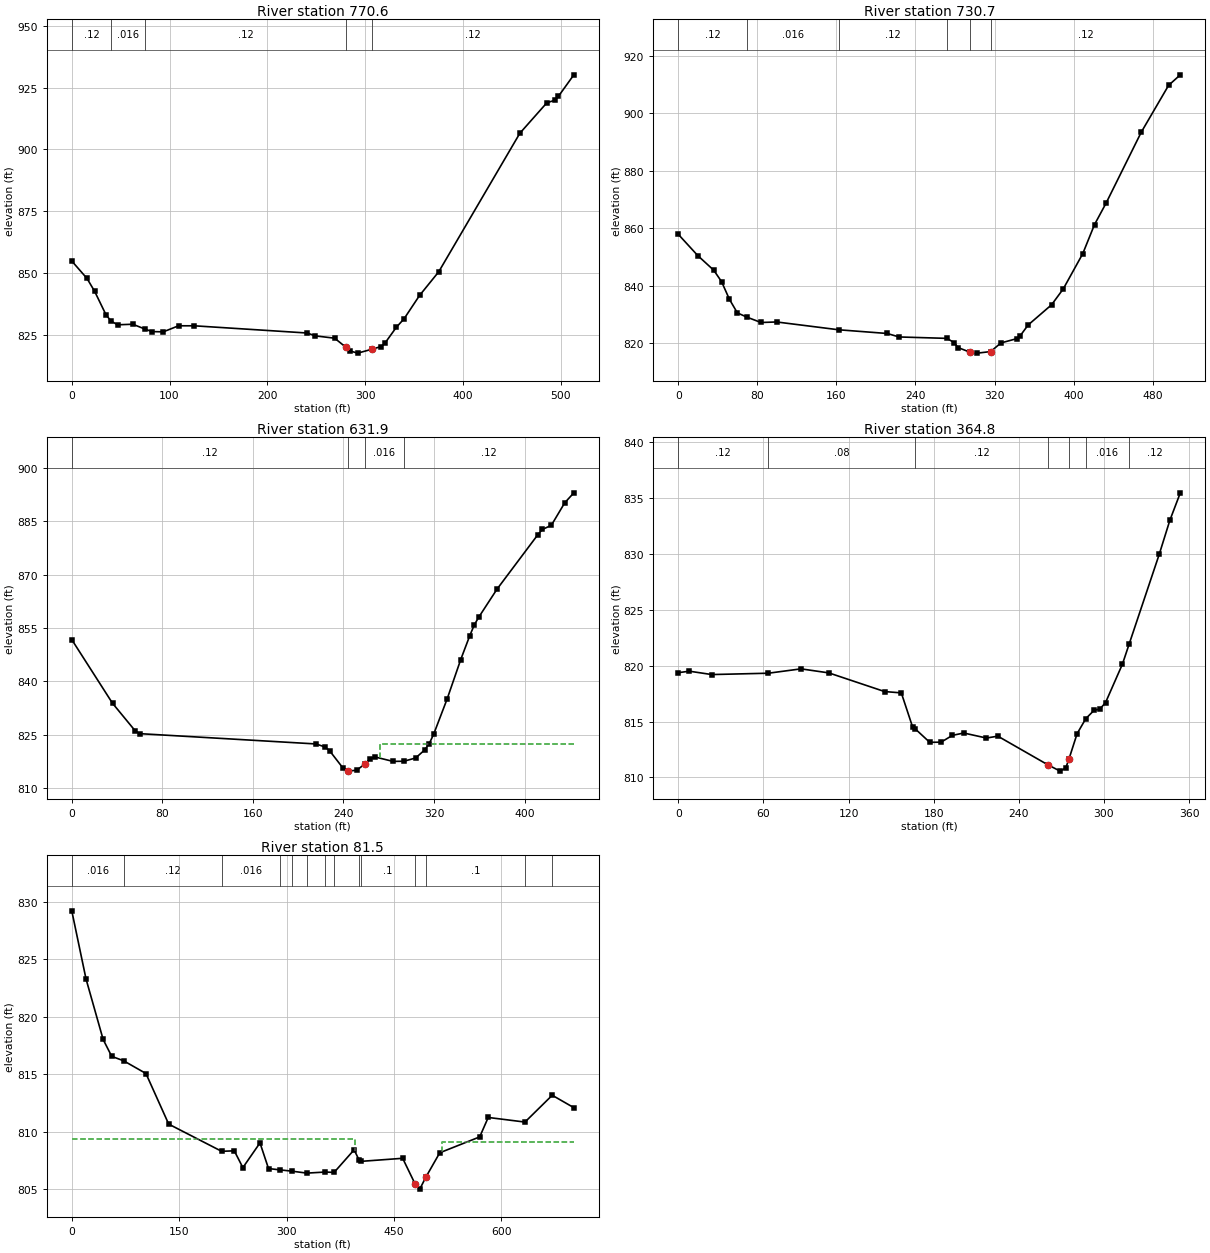
Type RM Length L Ch R = 1 ,770.6   ,40.1,39.9,40.4
XS GIS Cut Line= 4
     1778484.883      385946.597     1778578.661        386002.6
     1778579.258      386158.211     1778773.474      386313.377
#Sta/Elev= 30
       0  854.76    15.6  847.69    23.4  842.47    35.1  832.91   40.18830.4627
    46.8  828.93    62.4  829.16   74.58827.2426    81.9  826.18    93.6  826.08
   109.2  828.53   125.2  828.53   240.9   825.6   248.9  824.45   268.8  823.51
   280.6  819.74   284.6  818.33   292.4  817.46   307.4  819.09   316.1  820.11
   320.1  821.43   331.9  827.93   339.8  831.37   355.6   840.8   375.3  850.44
   458.2  906.51   485.8  918.84   493.7  919.83   497.6  921.44   513.4  930.16
#Mann= 5 ,-1 , 0
       0     .12       0   40.18    .016       0   74.58     .12       0
   280.6    .045       0   307.4     .12       0
Bank Sta=280.6,307.4
XS Rating Curve= 0 ,0
Exp/Cntr=0.3,0.1

Type RM Length L Ch R = 1 ,730.7   ,98.9,98.8,98.9
XS GIS Cut Line= 4
     1778458.834      385966.134     1778542.192      386013.021
       1778539.1      386176.663     1778733.315      386331.829
#Sta/Elev= 30
       0   857.9    19.9  850.43    35.9  845.39    43.8  841.43    51.8  835.24
    59.8  830.53   69.47829.0408    83.7  827.18    99.6  827.36  162.29824.6414
   211.4  823.35   223.4  822.14  271.88821.6467     279  820.19     283  818.46
   294.8  816.88   302.7  816.51     316  817.05   326.4  820.05   342.2  821.53
   346.1  822.64     354  826.32   377.7  833.36   389.5  838.88   409.2  851.14
   421.1  861.27   432.9  868.81   468.4  893.46   496.1  909.79   507.9  913.43
#Mann= 6 ,-1 , 0
       0     .12       0   69.47    .016       0  162.29     .12       0
  271.88    .016       0   294.8    .045       0     316     .12       0
Bank Sta=294.8,316
XS Rating Curve= 0 ,0
Exp/Cntr=0.3,0.1

Type RM Length L Ch R = 1 ,631.9   ,267.3,267.1,255.8
XS GIS Cut Line= 2
     1778319.724      386127.056      1778666.24        386403.9
#Sta/Elev= 30
       0   851.7      36   833.8    55.9   826.1    59.9  825.26   215.8  822.36
   223.8   821.5   227.8  820.43   239.7  815.53   243.7  814.72   251.7  814.97
   258.7  816.68   263.7  818.18   267.7  818.72   283.7  817.46  293.37817.4992
   303.7  818.41   311.7  820.66   315.7  822.41   319.7  825.12   331.6  835.04
   343.6  846.11   351.6  852.83   355.6  855.87   359.6  858.06   375.6  865.88
   411.6  881.16   415.6  882.67   423.6  883.84   435.5   890.2   443.5  892.98
#Mann= 4 ,-1 , 0
       0     .12       0   243.7    .045       0   258.7    .016       0
  293.37     .12       0
#XS Ineff= 2 , 0
                          272.47          822.26
Permanent Ineff=
       F       F
Bank Sta=243.7,258.7
XS Rating Curve= 0 ,0
Exp/Cntr=0.3,0.1

Type RM Length L Ch R = 1 ,364.8   ,278,283.3,295.2
XS GIS Cut Line= 4
     1778279.102      386337.338     1778362.173      386470.838
     1778515.212       386500.14     1778552.115      386482.773
#Sta/Elev= 30
       0  819.38     7.9  819.51    23.6  819.21   63.47819.3303    86.5  819.72
   106.1  819.36   145.4  817.69   157.2  817.57   165.2   814.5  166.95814.3556
   177.2  813.15   185.2  813.16   193.2  813.77   201.2  813.98   217.2  813.53
   225.2   813.7   260.4  811.14   269.1  810.57   273.1  810.86   275.4  811.68
   281.1  813.93  287.24 815.272   293.1  816.02   297.1  816.12   301.1   816.7
     313  820.14  317.67821.9092     339  829.99   346.4     833   353.8  835.47
#Mann= 7 ,-1 , 0
       0     .12       0   63.47     .08       0  166.95     .12       0
   260.4    .045       0   275.4     .12       0  287.24    .016       0
  317.67     .12       0
Bank Sta=260.4,275.4
XS Rating Curve= 0 ,0
Exp/Cntr=0.3,0.1

Type RM Length L Ch R = 1 ,81.5    ,83.9,81.5,79.2
XS GIS Cut Line= 3
     1778127.235      386314.678     1778159.202      386595.671
      1778483.74      386859.898
#Sta/Elev= 30
       0  829.19    19.9  823.27    43.8  818.01    55.8  816.54   72.42 816.156
   103.6  815.05   135.4  810.65  209.37808.2867     227  808.33     239  806.87
   262.9  809.02   274.8  806.79  290.23806.6771  307.58806.5612  328.32806.3914
  354.36806.4864  366.41806.4516   394.4  808.42  401.14807.5475   404.5807.4163
   462.2  807.68   479.4  805.47   486.1     805   494.4  806.02     514  808.16
   569.8  809.54   581.7  811.23  633.02810.8289  671.11813.1599   701.3  812.08
#Mann= 14 ,-1 , 0
       0    .016       0   72.42     .12       0  209.37    .016       0
  290.23     .08       0  307.58    .016       0  328.32     .08       0
  354.36    .016       0  366.41     .06       0  401.14    .016       0
   404.5      .1       0   479.4    .045       0   494.4      .1       0
  633.02    .016       0  671.11      .1       0
#XS Ineff= 2 , 0
          395.25  809.32  517.81          809.08
Permanent Ineff=
       F       F
Bank Sta=479.4,494.4
XS Rating Curve= 0 ,0
Exp/Cntr=0.3,0.1

Chan Stop Cuts=-1
Use User Specified Reach Order=0
Composite Channel Slope=5